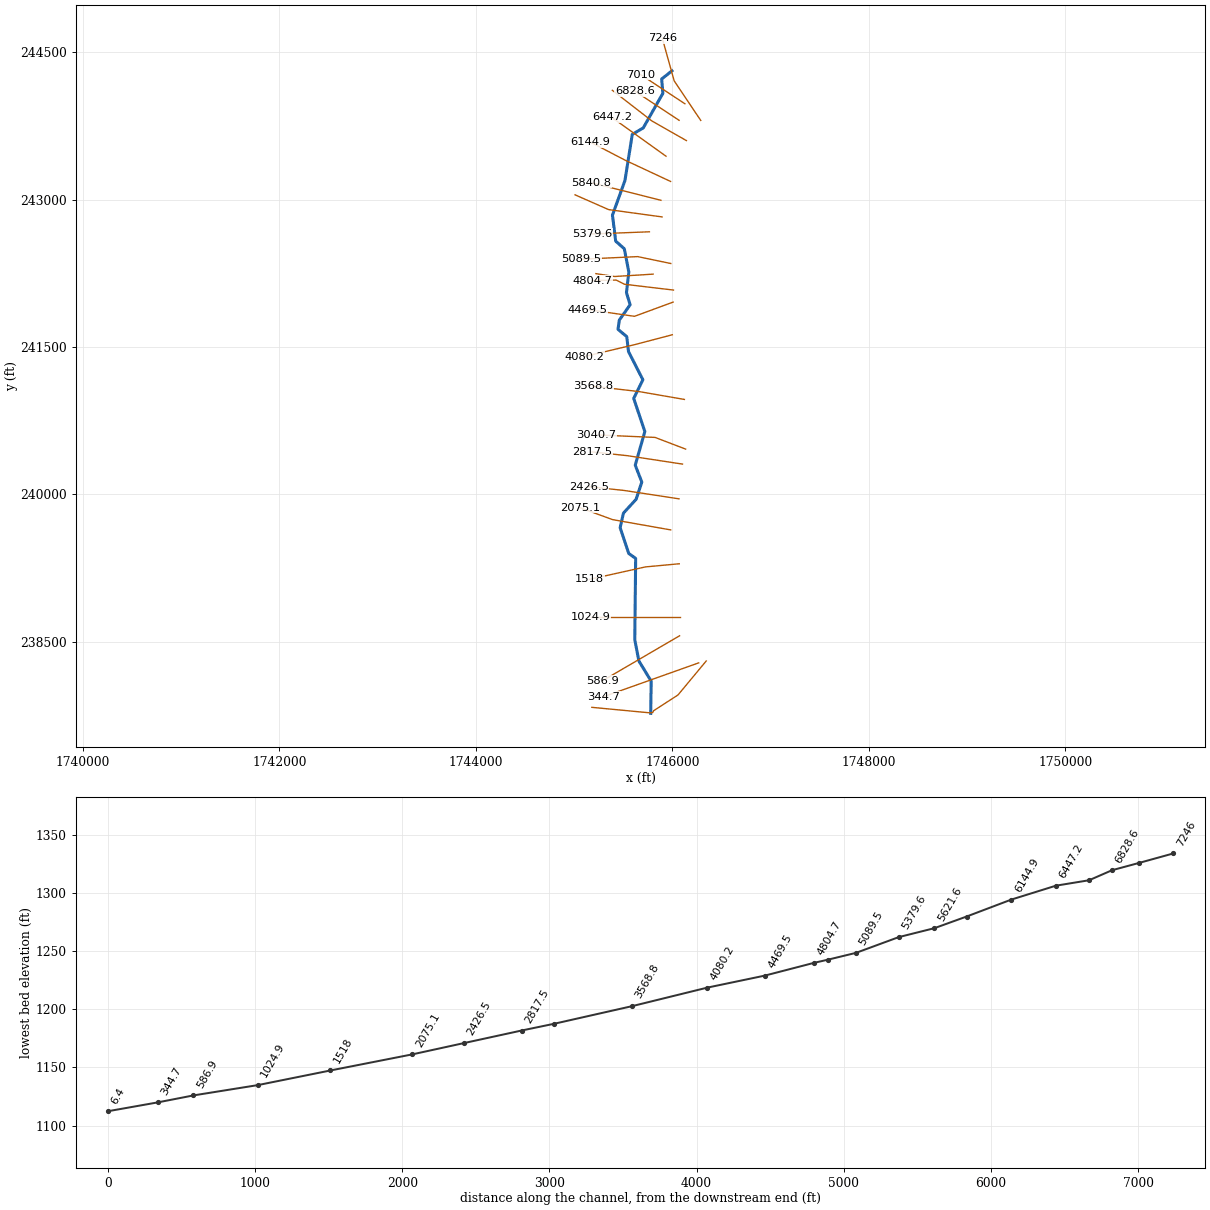
--- SycamorBr.prj (project) ---

Proj Title=SycamorBr
Current Plan=p01
Default Exp/Contr=0,0
English Units
Geom File=g01
Flow File=f01
Plan File=p01
BEGIN DESCRIPTION:
END DESCRIPTION:
DSS Export Rating Curves= 0
DSS Export Rating Curve Sorted= 0
DSS Export Volume Flow Curves= 0
DXF OffsetX= 0
DXF OffsetY= 0
DXF ScaleX= 0
DXF ScaleY= 0

--- SycamorBr.p01 (plan) ---

Plan Title=Floodplain
Program Version=4.00
Geom File=g01
Flow File=f01
K Sum by GR=0
Std Step Tol=0.01
Critical Tol=0.01
Num of Std Step Trials=20
Max Error Tol=0.3
Flow Tol Ratio=0.001
Split Flow NTrial=30
Split Flow Tol=0.02
Split Flow Ratio=0.02
Log Output Level=0
Friction Slope Method=1
Unsteady Friction Slope Method=2
Unsteady Bridges Friction Slope Method=1
Global Log Level=0
CheckData=False
Run HTab=0
Run UNet=0
Run PostProcess=0
UNET Theta=0
UNET Theta Warmup=0
UNET ZTol=0
UNET ZSATol=0
UNET MxIter=0
UNET MaxInSteps=0
UNET DtIC=0
UNET DtMin=0
UNET MaxCRTS=0
UNET WFStab=0
UNET SFStab=0
UNET WFX=0
UNET SFX=0
UNET DSS MLevel=0
UNET DZMax Abort=0
UNET Convert EG Bridges=0
UNET Use Existing IB Tables=0
UNET Froude Limit=0
UNET Froude Power=0
Write IC File=0
Echo Input=False
Echo Output=False
Write Detailed=0

--- SycamorBr.f01 (steady flow) ---

Flow Title=NFF Regression Equation
Program Version=4.00
Number of Profiles=1
Profile Names=P100yr
River Rch & RM=SycamorBr,Main      ,7246
636.4284
River Rch & RM=SycamorBr,Main      ,7010
414.7125
River Rch & RM=SycamorBr,Main      ,5840.8
696.8452
River Rch & RM=SycamorBr,Main      ,5840.8
459.5068
River Rch & RM=SycamorBr,Main      ,4080.2
755.2598
River Rch & RM=SycamorBr,Main      ,4080.2
505.2688
River Rch & RM=SycamorBr,Main      ,3040.7
795.9028
River Rch & RM=SycamorBr,Main      ,3040.7
538.1221
River Rch & RM=SycamorBr,Main      ,6.4
862.3615
River Rch & RM=SycamorBr,Main      ,6.4
590.7075
Boundary for River Rch & Prof#=SycamorBr,Main      ,1
Up Type=0
Dn Type=3
Dn Slope=0.022506

--- SycamorBr.g01 (geometry) ---

Geom Title=USGS 10m DEM
Program Version=4.00

River Reach=SycamorBr       ,Main
Reach XY= 30
     1745994.736      244310.674      1745889.72      244227.686
     1745902.434      244082.384     1745702.644      243730.026
     1745590.943      243663.732     1745516.355      243194.209
     1745389.336      242842.776     1745422.029        242577.6
     1745510.014      242499.867      1745555.76      242263.438
     1745531.847      242053.194     1745569.147      241930.098
     1745459.263      241774.806     1745445.641       241680.36
     1745534.925      241604.877     1745552.589      241453.599
     1745698.844      241166.766     1745605.473      240976.554
     1745718.971      240639.195     1745620.911      240297.266
     1745688.113      240125.629      1745630.04      239950.324
     1745500.955       239809.01     1745467.436      239660.662
     1745554.617      239399.119     1745625.452      239348.263
     1745616.452      238520.877     1745658.145      238304.813
     1745783.468      238098.666     1745778.404       237771.15

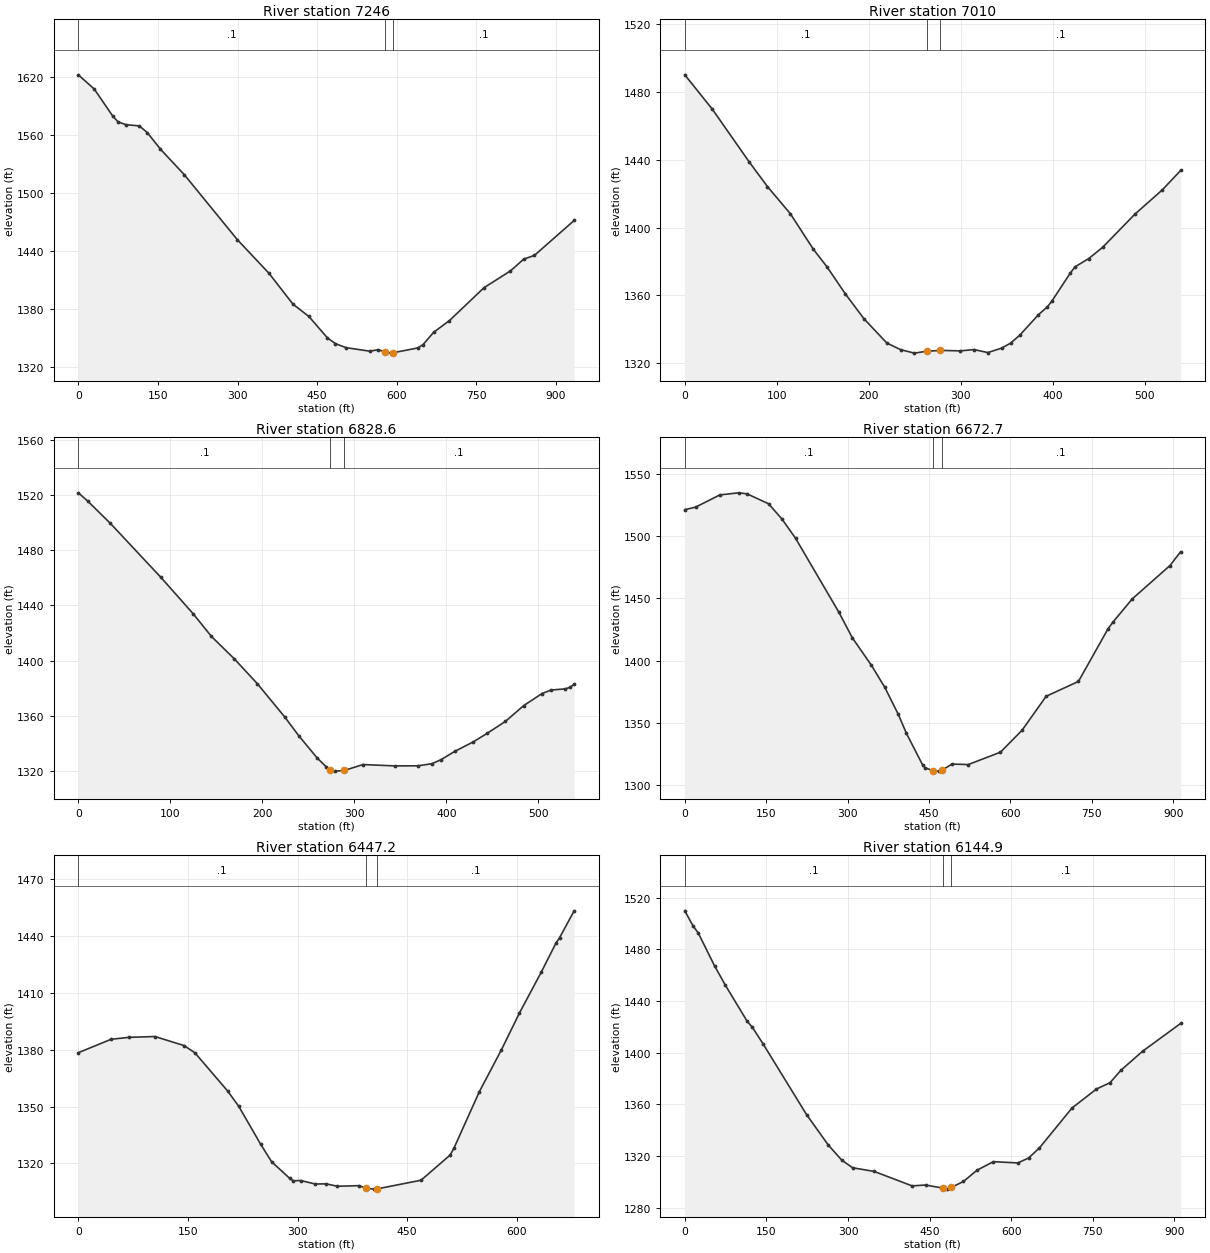
Type RM Length L Ch R = 1 ,7246    ,221,236,249.3
XS GIS Cut Line= 3
     1746287.677      243806.462     1746017.657      244208.547
     1745896.608      244641.776
#Sta/Elev= 30
       0 1621.84      30 1607.15    64.9 1579.14    74.9 1573.24    89.9 1570.29
   114.8  1569.1   129.8 1562.23   154.8 1544.96   199.7 1518.62   299.6  1451.5
   359.5 1416.56   404.4 1384.84   434.4 1372.13   469.4 1349.93   484.3 1344.08
   504.3  1339.9   549.3 1336.24   564.3 1337.77   578.6 1335.65   589.3 1334.24
   593.6 1334.69   639.3 1339.57   649.3 1342.93   669.3 1355.71   699.2 1367.87
   764.2 1401.79   814.2 1419.24   839.2 1431.37   859.2 1435.18   934.2 1471.36
#Mann= 3 , 0 , 0
       0      .1       0   578.6    .045       0   593.6      .1       0
Bank Sta=578.6,593.6
XS Rating Curve= 0 ,0
Exp/Cntr=0.3,0.1

Type RM Length L Ch R = 1 ,7010    ,179.4,181.4,185.1
XS GIS Cut Line= 2
      1746126.34      243975.922     1745676.355      244272.464
#Sta/Elev= 30
       0  1490.1    29.9 1469.84    69.9 1438.81    89.8 1424.22   114.8 1408.13
   139.7 1387.26   154.7 1376.74   174.6 1360.85   194.6 1346.32   219.6 1331.92
   234.5 1328.03   249.5 1325.97   262.7 1327.05   277.7 1327.59   299.4  1327.3
   314.4 1328.06   329.3  1326.3   344.3 1328.91   354.3 1331.92   364.3 1336.67
   384.2 1348.55   394.2 1353.35   399.2 1356.84   419.2 1373.35   424.1 1376.84
   439.1 1381.77   454.1 1388.36     489 1407.82     519 1422.24   538.9  1433.7
#Mann= 3 , 0 , 0
       0      .1       0   262.7    .045       0   277.7      .1       0
Bank Sta=262.7,277.7
XS Rating Curve= 0 ,0
Exp/Cntr=0.3,0.1

Type RM Length L Ch R = 1 ,6828.6  ,157.7,155.8,153.9
XS GIS Cut Line= 2
     1746067.412      243807.639     1745617.427      244104.181
#Sta/Elev= 30
       0 1521.71      10 1515.85    34.9 1499.49    89.8 1460.31   124.8 1433.97
   144.7 1417.47   169.7 1401.13   194.6 1383.18   224.6 1358.84   239.5  1345.5
   259.5 1329.38   269.4 1322.87     274 1320.85   279.4 1319.76     289 1320.23
   309.4 1324.53   344.3 1323.55   369.2 1323.63   384.2 1325.13   394.2 1328.08
   409.2 1334.12   429.1 1340.93   444.1 1347.09   464.1  1355.8     484 1367.27
     504 1376.08     514 1378.62   528.9 1379.43   533.9 1380.45   538.9 1382.69
#Mann= 3 , 0 , 0
       0      .1       0     274    .045       0     289      .1       0
Bank Sta=274,289
XS Rating Curve= 0 ,0
Exp/Cntr=0.3,0.1

Type RM Length L Ch R = 1 ,6672.7  ,223.3,225.5,227.3
XS GIS Cut Line= 3
     1746141.998       243600.98     1745791.294      243800.345
     1745387.872      244112.957
#Sta/Elev= 30
       0 1521.26    19.9  1523.3    64.7 1533.14    99.6 1534.79   114.6    1534
   154.4 1525.99   179.3  1513.6   204.2 1498.22   283.9 1438.87   308.8 1418.26
   343.6  1396.4   368.6 1378.47   393.4 1356.81   408.4 1341.55   438.1 1316.29
     443 1313.81   458.3 1311.34   467.8 1311.14   473.3 1311.72   492.6 1316.84
   522.3 1316.41   581.8 1326.38   621.4  1343.9     666 1371.29   725.5 1383.23
     780 1425.51   789.9 1431.31   824.6 1449.54     894 1476.29   913.8  1487.4
#Mann= 3 , 0 , 0
       0      .1       0   458.3    .045       0   473.3      .1       0
Bank Sta=458.3,473.3
XS Rating Curve= 0 ,0
Exp/Cntr=0.3,0.1

Type RM Length L Ch R = 1 ,6447.2  ,299.4,302.3,305.7
XS GIS Cut Line= 2
     1745934.791      243441.737     1745383.085      243836.551
#Sta/Elev= 30
       0  1378.5    44.9 1385.61    69.8 1386.63   104.8 1387.05   144.7 1382.27
   159.6 1378.42   204.5 1358.18   219.5 1350.19   249.4 1330.21   264.4 1320.94
   289.3  1312.1   294.3 1310.85   304.3    1311   324.2 1309.15   339.2 1309.24
   354.2 1307.98   384.1 1308.28   393.8 1306.91   404.1 1306.45   408.8 1306.57
   468.9 1311.16   508.8 1324.48   513.8 1327.99   548.7 1357.93   578.7 1379.92
   603.6 1399.51   633.5 1421.14   653.5  1436.4   658.5 1439.28   678.4 1453.44
#Mann= 3 , 0 , 0
       0      .1       0   393.8    .045       0   408.8      .1       0
Bank Sta=393.8,408.8
XS Rating Curve= 0 ,0
Exp/Cntr=0.3,0.1

Type RM Length L Ch R = 1 ,6144.9  ,299.5,304.1,308.9
XS GIS Cut Line= 3
      1745981.11        243185.1     1745517.165      243402.082
     1745163.114      243586.322
#Sta/Elev= 30
       0 1509.71    14.9 1498.25    24.9 1492.44    54.7 1467.16    74.6 1452.15
   114.4 1424.47   124.3 1419.57   144.2 1406.61   223.8 1352.13   263.6 1328.68
   288.4 1316.98   308.3 1311.05   348.1 1308.19   417.7 1297.02   442.6 1297.69
   474.6 1295.27   482.3 1294.51   489.6 1295.81   512.2 1300.44   537.1 1309.14
   567.1 1315.73     612 1314.77   631.9 1318.58   651.9 1326.43   711.7 1357.25
   756.6 1371.92   781.6 1376.82   801.5 1386.41   841.4 1401.14   911.3 1422.62
#Mann= 3 , 0 , 0
       0      .1       0   474.6    .045       0   489.6      .1       0
Bank Sta=474.6,489.6
XS Rating Curve= 0 ,0
Exp/Cntr=0.3,0.1

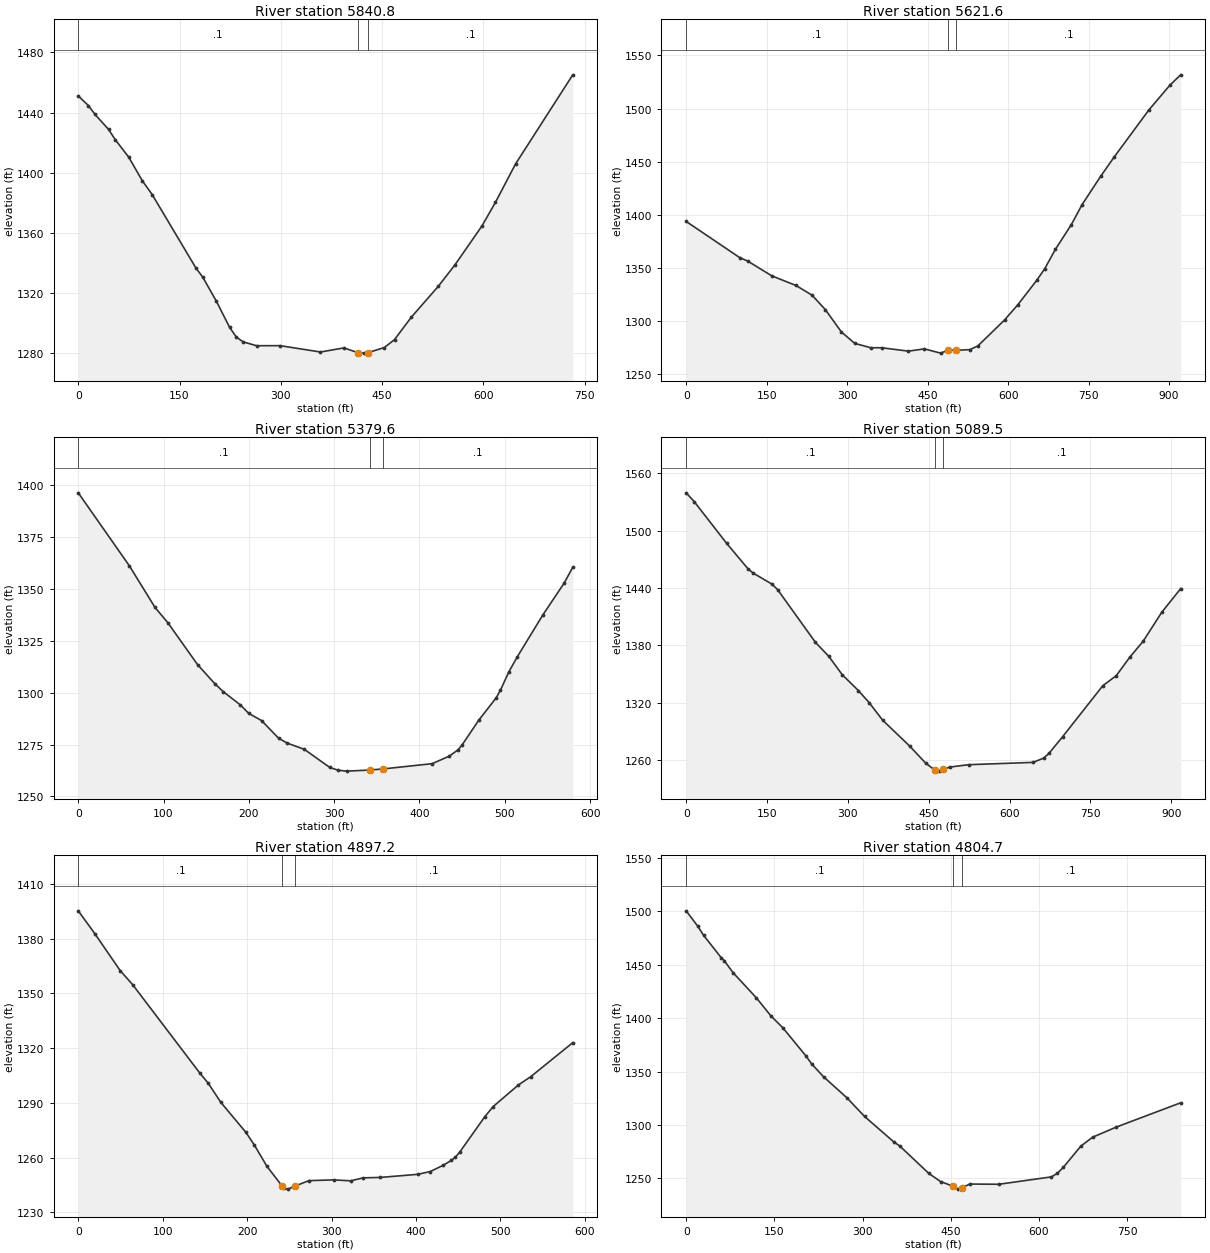
Type RM Length L Ch R = 1 ,5840.8  ,216.8,219.2,221.3
XS GIS Cut Line= 2
      1745882.67      242993.475     1745172.349      243172.779
#Sta/Elev= 30
       0 1451.11      15 1444.67    24.9 1438.74    44.8 1428.85    54.8 1421.98
    74.8 1410.31    94.7 1394.78   109.6 1385.36   174.4 1336.49   184.4 1330.51
   204.3  1314.7   224.3 1297.02   234.2 1290.57   244.2 1287.42   264.1 1284.84
     299 1284.88   358.8 1280.66   393.7 1283.39   414.2 1280.22   423.6 1279.91
   429.2 1280.21   453.5 1283.65   468.5 1288.89   493.4 1303.82   533.3 1324.34
   558.2 1338.75     598  1364.5     618 1380.24   647.9 1405.87   732.6 1465.13
#Mann= 3 , 0 , 0
       0      .1       0   414.2    .045       0   429.2      .1       0
Bank Sta=414.2,429.2
XS Rating Curve= 0 ,0
Exp/Cntr=0.3,0.1

Type RM Length L Ch R = 1 ,5621.6  ,237.7,242.1,246.4
XS GIS Cut Line= 3
     1745893.668      242824.274     1745349.929       242898.65
     1745008.713      243048.849
#Sta/Elev= 30
       0 1393.77    99.8 1359.73   114.8 1356.45   159.6 1342.56   204.6 1333.52
   234.5 1324.43   259.4 1310.78   289.4 1289.68   314.3 1278.97   344.2 1274.92
   364.2 1274.92   414.1 1271.73     444 1273.87     474 1269.86   488.5 1272.59
   503.5 1272.55   528.8 1273.15   543.8 1276.75   593.5 1301.15   618.4 1315.59
   653.2 1338.32   668.1 1349.22     688 1367.45   717.8 1390.77   737.7 1409.51
   772.5 1436.29   797.3 1454.18     862 1498.52   901.7 1522.13   921.6 1531.76
#Mann= 3 , 0 , 0
       0      .1       0   488.5    .045       0   503.5      .1       0
Bank Sta=488.5,503.5
XS Rating Curve= 0 ,0
Exp/Cntr=0.3,0.1

Type RM Length L Ch R = 1 ,5379.6  ,289.9,290.1,290.2
XS GIS Cut Line= 2
     1745765.433      242672.796     1745186.141      242650.383
#Sta/Elev= 30
       0  1396.4      60 1361.13      90 1341.11     105 1333.76   139.9 1313.52
   159.9 1304.42   169.9 1300.52   189.9 1294.16   199.9 1290.02   214.9 1286.56
   234.9 1278.03   244.9 1275.69   264.9 1272.72   294.9 1263.94   304.9 1262.58
   314.8 1262.18   342.1 1262.71   357.1 1263.23   414.8 1265.77   434.8 1269.39
   444.8 1272.32   449.8 1274.72   469.8 1286.92   489.8 1297.45   494.8 1301.11
   504.8 1310.09   514.8  1317.4   544.7 1337.56   569.7 1352.92   579.7 1360.52
#Mann= 3 , 0 , 0
       0      .1       0   342.1    .045       0   357.1      .1       0
Bank Sta=342.1,357.1
XS Rating Curve= 0 ,0
Exp/Cntr=0.3,0.1

Type RM Length L Ch R = 1 ,5089.5  ,192,192.3,192.6
XS GIS Cut Line= 3
      1745982.93      242350.038     1745645.578      242420.154
     1745073.376      242393.495
#Sta/Elev= 30
       0 1539.44      15 1530.17    74.9 1486.78   114.8 1459.96   124.8 1455.39
   159.8 1443.83   169.8 1438.14   239.7 1383.28   264.7 1368.48   289.6 1349.31
   319.6 1332.76   339.6 1320.08   364.5 1301.86   414.3    1275   444.2 1257.06
   461.4 1249.62   469.1 1248.64   476.4 1250.38     489 1252.86   523.9 1255.36
   643.4 1257.78   663.4  1262.3   673.3  1267.4   698.2  1284.5   772.9  1337.9
   797.8 1348.36   822.7 1367.46   847.6 1384.27   882.5 1414.78   917.4 1439.37
#Mann= 3 , 0 , 0
       0      .1       0   461.4    .045       0   476.4      .1       0
Bank Sta=461.4,476.4
XS Rating Curve= 0 ,0
Exp/Cntr=0.3,0.1

Type RM Length L Ch R = 1 ,4897.2  ,96.5,92.5,88.4
XS GIS Cut Line= 3
     1745803.363      242241.775     1745411.996      242217.638
     1745220.623      242246.947
#Sta/Elev= 30
       0 1395.28    19.8 1382.63    49.6 1362.55    64.5 1354.76   143.9 1306.37
   153.9  1300.8   168.8 1290.32   198.5 1273.86   208.5 1266.93   223.4 1255.25
   241.7 1244.27   243.2 1243.42   248.2 1242.71   256.7 1244.35     273 1247.36
   302.8 1247.78   322.6 1247.26   337.5 1248.89   357.4 1249.11     402 1250.82
   416.9 1252.35   431.8 1255.68   441.8 1258.45   446.7 1260.25   451.7 1262.92
   481.5 1282.41   491.4 1287.97   521.2 1299.78   536.1 1304.42   585.7 1323.01
#Mann= 3 , 0 , 0
       0      .1       0   241.7    .045       0   256.7      .1       0
Bank Sta=241.7,256.7
XS Rating Curve= 0 ,0
Exp/Cntr=0.3,0.1

Type RM Length L Ch R = 1 ,4804.7  ,334.7,335.3,335.8
XS GIS Cut Line= 4
     1746010.252      242079.711     1745511.435       242138.82
     1745427.513      242181.432     1745182.693       242176.26
#Sta/Elev= 30
       0 1500.31    19.9 1485.74    29.8 1477.29    59.7  1456.4    64.6 1453.79
    79.6 1442.56   119.4 1418.95   144.2    1402   164.1 1391.15   203.9 1364.49
   213.8 1356.94   233.8 1345.07   273.5 1325.43   303.4 1308.05   353.1 1284.26
     363 1280.56   412.8 1254.74   432.7 1247.18   453.8  1242.8   462.5 1240.05
   468.8 1241.15   482.4  1244.8     532  1244.6   621.4  1251.5   631.4 1254.84
   641.4 1260.28   671.4 1280.24   691.4 1288.59   731.4 1298.01   841.3  1320.8
#Mann= 3 , 0 , 0
       0      .1       0   453.8    .045       0   468.8      .1       0
Bank Sta=453.8,468.8
XS Rating Curve= 0 ,0
Exp/Cntr=0.3,0.1

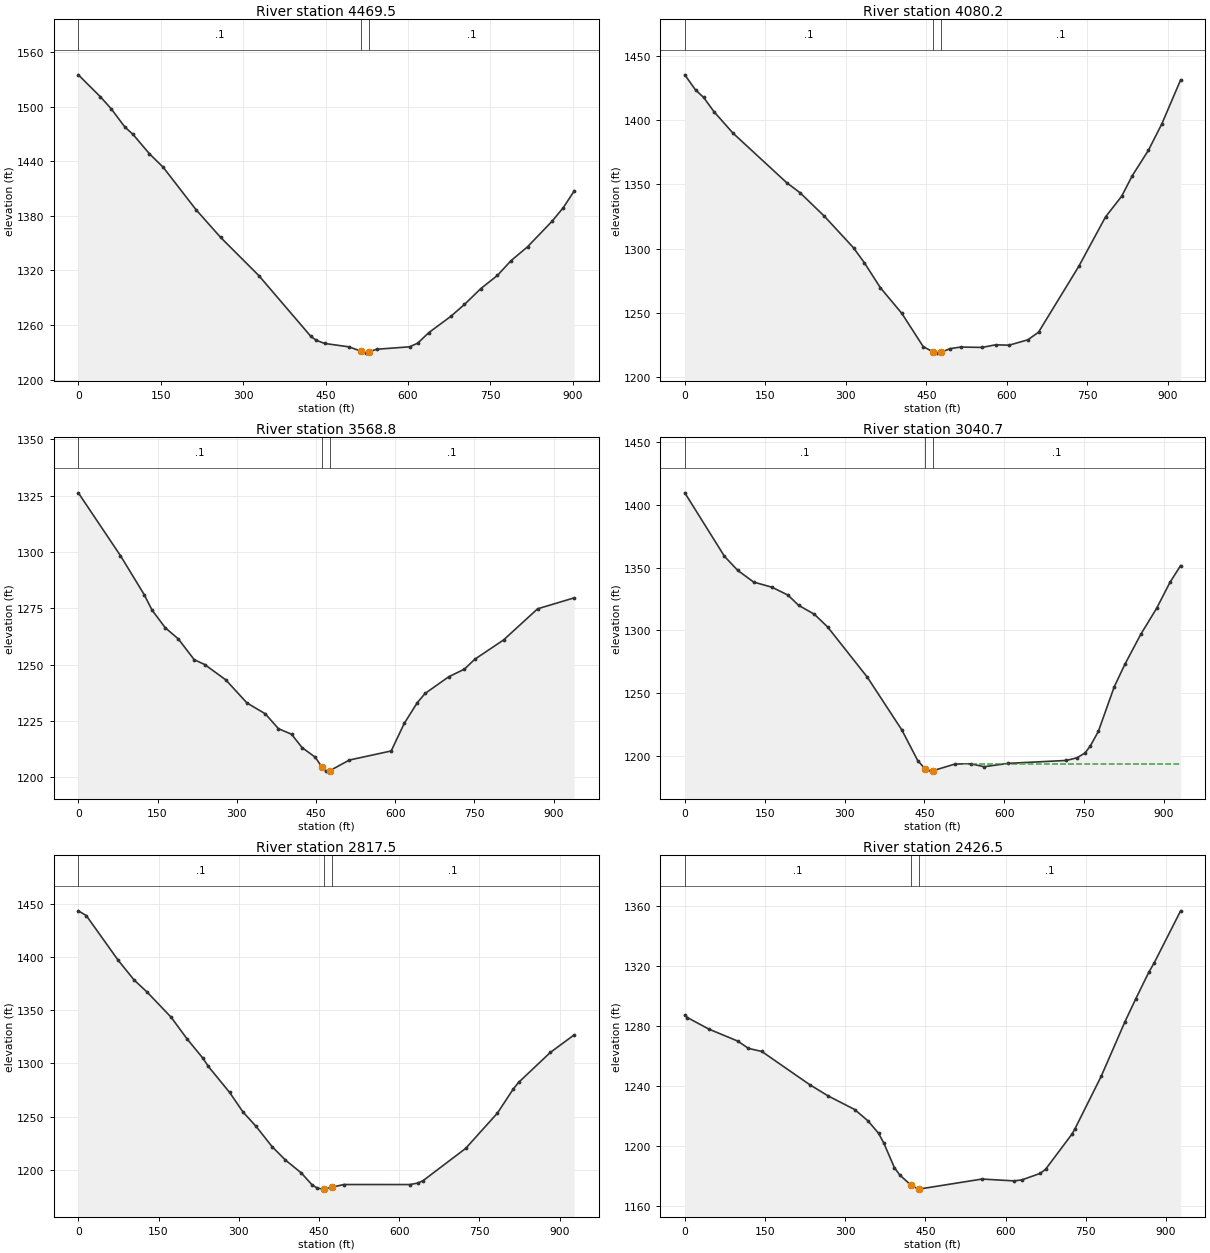
Type RM Length L Ch R = 1 ,4469.5  ,378.8,389.3,399.2
XS GIS Cut Line= 3
     1746006.166      241957.063     1745613.714      241812.479
     1745134.419      241881.442
#Sta/Elev= 30
       0 1535.06    39.8 1511.15    59.8 1497.75    84.6 1477.74    99.6 1469.51
   129.4 1448.26   154.4 1433.48   214.1 1386.84   258.9 1356.36   328.6 1314.27
   423.2 1247.48   433.2 1243.12   448.2 1239.69   493.1 1235.87   514.9 1231.03
   523.1 1229.03   529.9 1230.62     543 1233.29   602.9 1235.97   617.9 1240.04
   637.9 1251.58   677.8 1269.37   702.8 1282.56   732.7 1300.05   762.7  1314.4
   787.6 1330.73   817.6 1345.93   862.5  1374.2   882.5 1388.84   902.5 1407.29
#Mann= 3 , 0 , 0
       0      .1       0   514.9    .045       0   529.9      .1       0
Bank Sta=514.9,529.9
XS Rating Curve= 0 ,0
Exp/Cntr=0.3,0.1

Type RM Length L Ch R = 1 ,4080.2  ,520,511.4,504.4
XS GIS Cut Line= 3
     1745998.601      241624.771     1745617.162      241524.557
     1745101.908      241402.593
#Sta/Elev= 30
       0 1435.02      20 1423.28      35  1417.5    54.9 1406.12    89.9 1389.67
   189.7 1351.25   214.7 1343.41   259.6 1325.34   314.5 1300.55   334.5 1289.02
   364.4 1269.58   404.4 1249.63   444.3 1223.77   462.2 1219.82   469.3 1218.73
   477.2 1219.32   494.3 1222.24   514.3 1223.44   554.2 1223.18   579.2 1225.21
   604.2  1224.9   639.2 1229.08   659.1 1234.98   734.1 1286.16     784 1324.62
     814 1340.63     834 1356.76   863.9 1376.38   888.9 1396.93   923.9 1431.08
#Mann= 3 , 0 , 0
       0      .1       0   462.2    .045       0   477.2      .1       0
Bank Sta=462.2,477.2
XS Rating Curve= 0 ,0
Exp/Cntr=0.3,0.1

Type RM Length L Ch R = 1 ,3568.8  ,524.8,528.1,526.8
XS GIS Cut Line= 3
     1746121.412      240966.519     1745659.551      241046.593
     1745192.405      241100.412
#Sta/Elev= 30
       0 1326.23    79.8 1298.35   124.7 1281.09   139.6  1274.2   164.6 1266.39
   189.5 1261.39   219.4 1252.23   239.4 1250.05   279.3 1243.25   319.2 1233.05
   354.1 1228.19     379 1221.61   403.9 1219.11   423.9 1213.18   448.8 1208.93
   461.3 1204.53   468.8 1202.78   473.7 1202.77   476.3 1202.98   513.3 1207.69
   592.5 1211.72   617.2 1223.94     642 1233.17   656.8 1237.24   701.4 1244.62
   731.1    1248   750.9 1252.42   805.3 1260.96   869.7 1274.77     939 1279.64
#Mann= 3 , 0 , 0
       0      .1       0   461.3    .045       0   476.3      .1       0
Bank Sta=461.3,476.3
XS Rating Curve= 0 ,0
Exp/Cntr=0.3,0.1

Type RM Length L Ch R = 1 ,3040.7  ,226.6,223.2,219.7
XS GIS Cut Line= 3
     1746134.051      240460.962     1745823.094      240579.856
     1745225.276      240605.371
#Sta/Elev= 30
       0 1409.66    74.5 1359.03    99.4  1347.8   129.2 1338.49     164 1334.31
   193.8 1328.06   213.7 1319.94   243.5 1312.73   268.3 1302.65   342.9 1262.55
   407.7 1220.46   437.6    1196   451.6 1189.33   462.6 1187.64   466.6 1188.04
   507.4 1193.29   537.4 1193.47   562.3 1191.15   607.2 1193.82   716.9 1196.17
   736.8 1198.31   751.8 1202.12   761.7 1207.74   776.7 1219.26   806.6  1254.9
   826.6 1272.87   856.5 1296.83   886.4 1317.65   911.3 1338.27   931.3 1351.62
#Mann= 3 , 0 , 0
       0      .1       0   451.6    .045       0   466.6      .1       0
#XS Ineff= 2 , 0
                          522.26          1193.5
Permanent Ineff=
       F       F
Bank Sta=451.6,466.6
XS Rating Curve= 0 ,0
Exp/Cntr=0.3,0.1

Type RM Length L Ch R = 1 ,2817.5  ,391.2,391,391
XS GIS Cut Line= 3
     1746102.188      240308.338     1745542.806       240393.73
     1745183.276      240432.234
#Sta/Elev= 30
       0 1443.58    14.9  1439.1    74.5  1397.1   104.2 1378.58   129.1 1366.93
   173.7 1343.41   203.5    1323   233.3 1304.78   243.2 1297.17   282.9  1272.8
   307.8 1254.45   332.6 1240.72   362.4 1221.75   387.2 1209.21     417 1197.02
   436.8 1186.05   446.7 1182.75   456.7 1181.77   459.2 1181.84   474.2  1183.5
   496.4  1186.1   620.4 1186.08   635.2 1187.52   645.1 1189.85   724.4 1220.05
   783.8 1253.25   813.5 1275.95   823.4 1282.14   882.9 1310.39   927.4 1326.88
#Mann= 3 , 0 , 0
       0      .1       0   459.2    .045       0   474.2      .1       0
Bank Sta=459.2,474.2
XS Rating Curve= 0 ,0
Exp/Cntr=0.3,0.1

Type RM Length L Ch R = 1 ,2426.5  ,352,351.4,350.8
XS GIS Cut Line= 3
     1746067.263      239954.707     1745507.881      240040.099
     1745148.351      240078.603
#Sta/Elev= 30
       0 1287.36       5 1285.69    44.7 1278.05    99.3 1269.94   119.1  1265.1
     144 1263.05   233.3 1240.92     268 1233.32   317.7 1224.22   342.5 1216.68
   362.4 1208.33   372.3 1201.69   392.1  1185.3   402.1 1180.45   422.9 1173.64
   436.8 1170.97   437.9 1170.99   555.9 1177.71   615.4 1176.49   630.2 1177.11
   664.9 1181.52   674.8 1184.25   724.4 1207.89   729.3 1211.01   778.8  1246.4
   823.4 1283.03   843.2 1298.04     868 1316.12   877.9 1322.25   927.4  1357.1
#Mann= 3 , 0 , 0
       0      .1       0   422.9    .045       0   437.9      .1       0
Bank Sta=422.9,437.9
XS Rating Curve= 0 ,0
Exp/Cntr=0.3,0.1

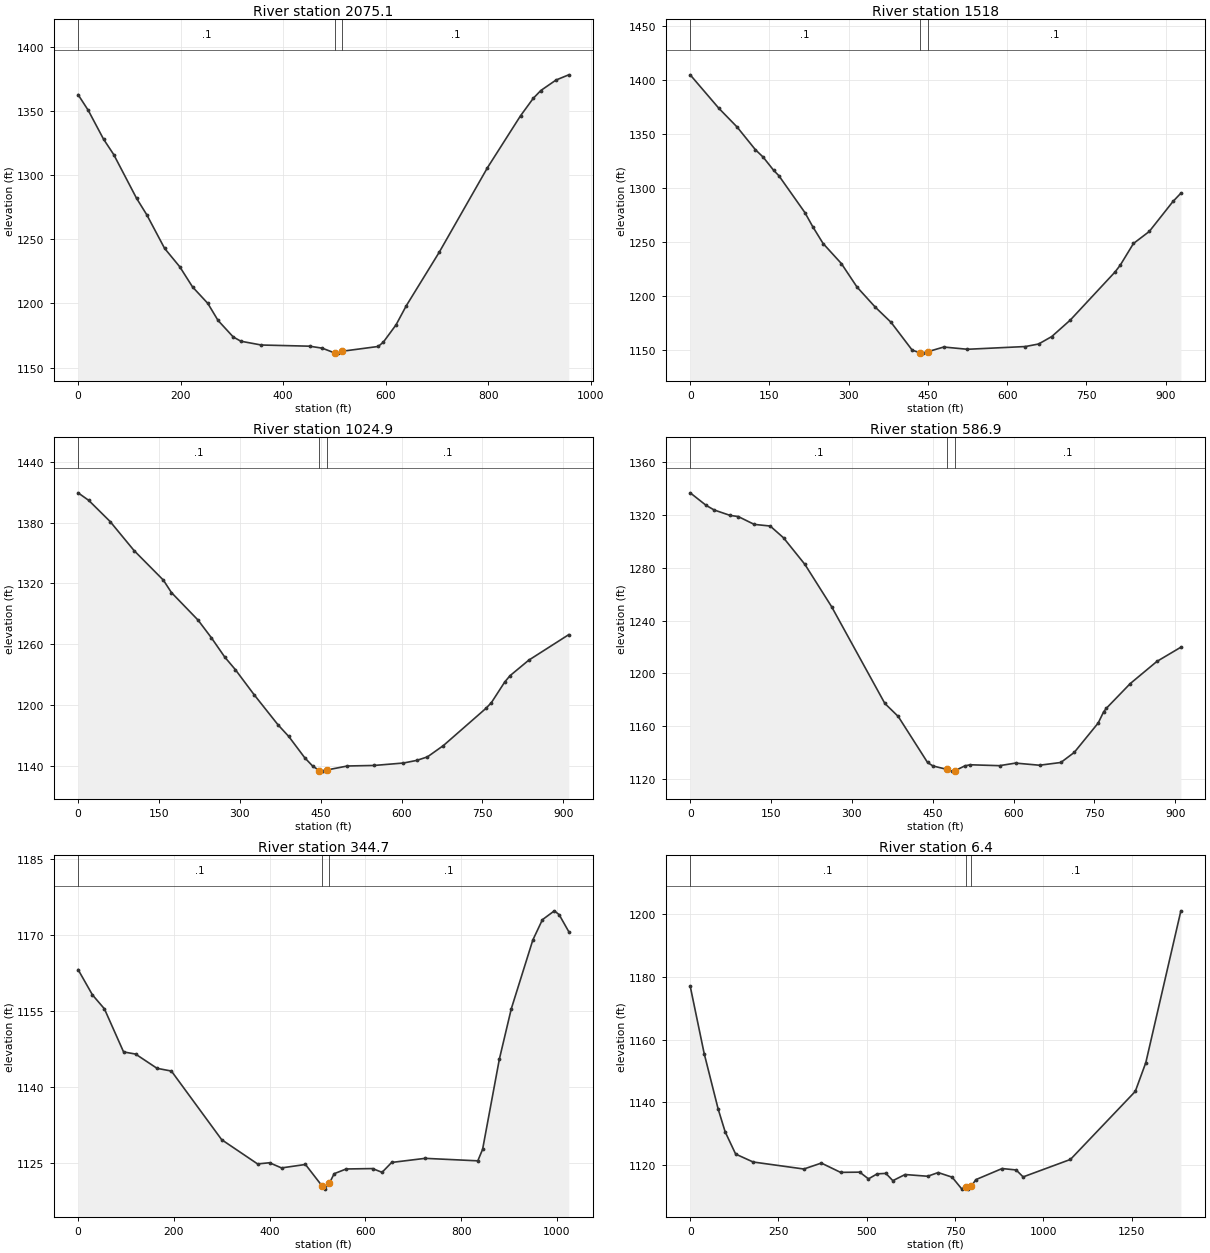
Type RM Length L Ch R = 1 ,2075.1  ,549,557.1,565.2
XS GIS Cut Line= 3
     1745982.078      239638.565     1745390.924      239743.101
     1745055.918      239865.314
#Sta/Elev= 30
       0 1362.75    19.8 1350.53    49.6 1328.09    69.5 1316.04   114.1  1281.9
     134 1269.07   168.7 1242.93   198.4  1228.5   223.3  1212.8     253 1200.02
   272.9 1186.76   302.6 1173.84   317.5 1170.52   357.2 1167.57   451.5 1166.65
   476.3 1165.09   500.5 1161.36   506.1 1161.24   515.5 1162.72   585.4 1166.44
   595.4 1169.86   620.1 1183.31     640 1198.13   704.3  1239.9   798.4 1305.81
   862.8 1346.23   887.6 1359.83   902.4 1365.95   932.2 1374.15   956.9 1378.18
#Mann= 3 , 0 , 0
       0      .1       0   500.5    .045       0   515.5      .1       0
Bank Sta=500.5,515.5
XS Rating Curve= 0 ,0
Exp/Cntr=0.3,0.1

Type RM Length L Ch R = 1 ,1518    ,498.1,493.1,488
XS GIS Cut Line= 3
     1746068.956      239293.892     1745725.013      239261.891
     1745155.287      239135.255
#Sta/Elev= 30
       0 1404.59    54.3 1373.64    88.8 1356.36   123.4 1335.41   138.2 1328.51
   157.9 1316.39   167.8 1311.42   217.1 1277.33   231.9 1264.36   251.7 1248.64
   286.2 1230.19   315.8 1208.48   350.4 1189.88   380.4 1175.79   420.2 1150.21
   435.5 1147.49   440.2 1147.36   450.5 1148.77   480.1    1153     525 1150.92
   634.8 1153.46   659.7  1155.8   684.6 1162.68   719.6 1177.88   804.4 1222.35
   814.3 1228.66   839.3  1248.7   869.2 1259.78   914.1 1287.51   929.1 1295.19
#Mann= 3 , 0 , 0
       0      .1       0   435.5    .045       0   450.5      .1       0
Bank Sta=435.5,450.5
XS Rating Curve= 0 ,0
Exp/Cntr=0.3,0.1

Type RM Length L Ch R = 1 ,1024.9  ,426,438,450.1
XS GIS Cut Line= 3
     1746076.887      238750.967     1745621.887      238750.967
     1745166.887      238750.967
#Sta/Elev= 30
       0 1409.31    19.8 1401.85    59.4 1381.02   103.9 1352.32   158.3 1323.12
   173.1 1310.96   222.6 1283.71   247.3 1266.29     272 1247.31   291.8 1234.82
   326.4 1210.23   370.9  1180.4   390.7 1168.99   420.4 1147.94   435.2 1139.68
   447.5 1135.31     455 1134.77   462.5 1136.02   499.5 1139.84     549 1140.36
   603.4 1142.77   628.1 1145.36   647.9 1148.82   677.6 1160.03   756.7 1196.82
   766.6  1202.4   791.3 1222.73   801.2 1228.97   835.8 1244.22     910 1269.41
#Mann= 3 , 0 , 0
       0      .1       0   447.5    .045       0   462.5      .1       0
Bank Sta=447.5,462.5
XS Rating Curve= 0 ,0
Exp/Cntr=0.3,0.1

Type RM Length L Ch R = 1 ,586.9   ,246.5,242.2,237.9
XS GIS Cut Line= 3
     1746072.268      238560.957     1745679.138      238331.388
     1745285.791      238102.152
#Sta/Elev= 30
       0 1336.89    29.7 1327.34    44.5 1323.88    74.2 1319.75    89.1 1318.91
   118.8 1312.96   148.4 1311.72   173.2 1302.78   212.8 1282.64   262.3 1250.62
   361.2 1177.19     386 1167.34   440.4 1132.46   450.3 1129.82   476.2 1127.23
   484.9 1125.88   491.2  1126.2   509.7 1129.88   519.6 1130.69     574 1130.02
   603.7 1131.97   648.2 1130.35   687.8 1132.44   712.6 1140.05   757.1 1162.38
     767  1170.7     772 1173.44   816.5 1192.24     866 1209.06   910.5 1219.84
#Mann= 3 , 0 , 0
       0      .1       0   476.2    .045       0   491.2      .1       0
Bank Sta=476.2,491.2
XS Rating Curve= 0 ,0
Exp/Cntr=0.3,0.1

Type RM Length L Ch R = 1 ,344.7   ,384.5,338.2,346.1
XS GIS Cut Line= 2
     1746266.957      238285.183     1745301.613      237941.786
#Sta/Elev= 30
       0 1163.25      30 1158.25      55 1155.49      95 1146.98     120 1146.56
   164.9 1143.74   194.9  1143.2   299.9 1129.64   374.8 1124.86   399.8 1125.09
   424.8 1124.07   474.8 1124.75   509.5 1120.51   514.8 1119.88   524.5 1121.01
   534.8 1122.93   559.8 1123.86   614.8 1123.94   634.8  1123.2   654.8 1125.15
   724.7 1125.96   834.7 1125.47   844.7 1127.74   879.7 1145.56   904.6  1155.5
   949.6 1169.09   969.6  1173.1   994.6 1174.85  1004.6 1174.08  1024.6 1170.74
#Mann= 3 , 0 , 0
       0      .1       0   509.5    .045       0   524.5      .1       0
Bank Sta=509.5,524.5
XS Rating Curve= 0 ,0
Exp/Cntr=0.3,0.1

Type RM Length L Ch R = 1 ,6.4     ,8.5,6.4,9.4
XS GIS Cut Line= 6
     1746344.011      238304.672     1746055.897      237958.323
     1745807.491      237797.406     1745797.733      237777.888
     1745762.282      237777.291     1745179.297      237832.656
#Sta/Elev= 30
       0 1177.07    39.6 1155.56    79.2 1137.83      99 1130.57   128.7 1123.47
   178.2 1120.94   321.8  1118.7   371.3  1120.6   425.8 1117.63   480.1  1117.7
   504.8 1115.55   529.4 1117.16   554.1  1117.3   573.8 1114.98   608.4 1116.94
   672.5 1116.39   702.1 1117.57   741.6  1116.1   768.3 1112.43   780.9  1112.8
     786 1112.28   795.9 1113.18   808.7  1115.3   883.2 1118.85   922.9  1118.4
   942.7 1116.18  1076.7 1121.76  1260.3 1143.48  1290.1 1152.67  1389.4 1201.12
#Mann= 3 , 0 , 0
       0      .1       0   780.9    .045       0   795.9      .1       0
Bank Sta=780.9,795.9
XS Rating Curve= 0 ,0
Exp/Cntr=0.3,0.1

Chan Stop Cuts=-1
Use User Specified Reach Order=0